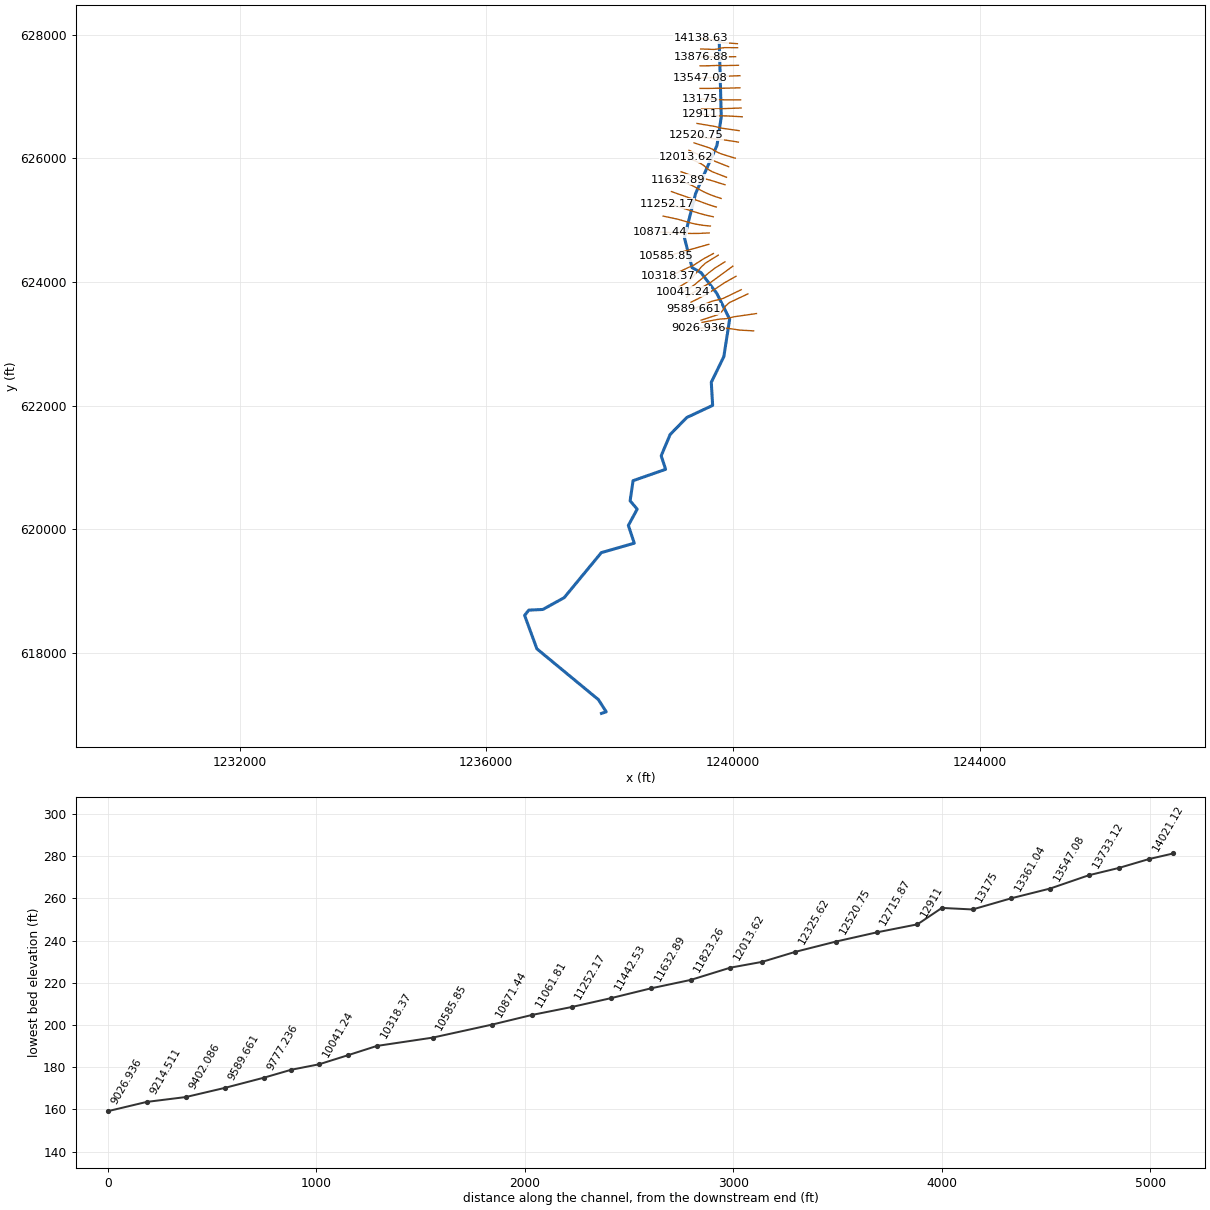
--- 337_ras.prj (project) ---

Proj Title=337
Current Plan=p01
Default Exp/Contr=0.3,0.1
English Units
Geom File=g01
Flow File=f01
Plan File=p01
Y Axis Title=Elevation
X Axis Title(PF)=Main Channel Distance
X Axis Title(XS)=Station
BEGIN DESCRIPTION:
RFD model 337 exported to HEC-RAS
END DESCRIPTION:

--- 337_ras.p01 (plan) ---

Plan Title=Plan 01
Program Version=4.10
Short Identifier=Plan 01
Geom File=g01
Flow File=f01
Subcritical Flow
Calc Critical at every XS
Secant Critical Depth

--- 337_ras.f01 (steady flow) ---

Flow Title=Flow 01
Program Version=5.01
Number of Profiles= 5
Profile Names=10yr,25yr,50yr,100yr,500yr
River Rch & RM=337,43,14138.63
  523.44  653.37  786.99  878.83 1092.99
River Rch & RM=337,43,14021.12
   527.8  659.62  794.74  888.58 1106.86
River Rch & RM=337,43,13876.88
  540.07  677.22  816.56  916.08  1146.1
River Rch & RM=337,43,13733.12
   543.2  681.71  822.14  923.13 1156.19
River Rch & RM=337,43,13547.08
  556.95  701.53  846.74  954.28 1200.89
River Rch & RM=337,43,13361.04
  564.86  712.96  860.94   972.3 1226.85
River Rch & RM=337,43,   13175
  572.12  723.48  874.01  988.94 1250.86
River Rch & RM=337,43,13028.01
  585.31  742.64  897.83 1019.32 1294.88
River Rch & RM=337,43,   12911
  589.92  749.33  906.16 1029.97 1310.36
River Rch & RM=337,43,12715.87
  600.75  765.12  925.81 1055.14 1347.02
River Rch & RM=337,43,12520.75
  606.49  773.51  936.26 1068.55  1366.6
River Rch & RM=337,43,12325.62
  616.45  788.09  954.42  1091.9 1400.79
River Rch & RM=337,43,12165.89
  626.17  802.34  972.19 1114.81 1434.44
River Rch & RM=337,43,12013.62
  631.97  810.88  982.83 1128.55 1454.66
River Rch & RM=337,43,11823.26
  638.91  821.09  995.57 1145.03 1478.96
River Rch & RM=337,43,11632.89
  650.89  838.75 1017.61  1173.6 1521.21
River Rch & RM=337,43,11442.53
  659.07  850.85 1032.72 1193.23 1550.32
River Rch & RM=337,43,11252.17
  662.92  856.54 1039.83 1202.47 1564.06
River Rch & RM=337,43,11061.81
  670.13  867.23 1053.18 1219.86 1589.93
River Rch & RM=337,43,10871.44
  676.85   877.2 1065.65 1236.13 1614.19
River Rch & RM=337,43,10585.85
  686.38  891.38 1083.37 1259.29 1648.81
River Rch & RM=337,43,10318.37
  700.66  912.67 1110.01 1294.18 1701.13
River Rch & RM=337,43, 10179.8
  702.07  914.77 1112.63 1297.63  1706.3
River Rch & RM=337,43,10041.24
  706.95  922.06 1121.75 1309.61 1724.32
River Rch & RM=337,43,9907.615
  711.43  928.77 1130.15 1320.65 1740.95
River Rch & RM=337,43,9777.236
  714.85  933.89 1136.56 1329.09 1753.66
River Rch & RM=337,43,9589.661
  716.22  935.93 1139.12 1332.45 1758.73
River Rch & RM=337,43,9402.086
  752.83  990.97 1208.11 1423.61 1896.92
River Rch & RM=337,43,9214.511
  759.71 1001.35 1221.14  1440.9 1923.27
River Rch & RM=337,43,9026.936
   762.5 1005.56 1226.42 1447.92 1933.98
River Rch & RM=337,43,8924.101
  763.11  1006.5 1227.59 1449.47 1936.36
River Rch & RM=337,43,8762.936
 1029.35 1418.34 1747.17 2156.34 3048.95
River Rch & RM=337,43,8628.984
 1029.93 1419.26 1748.34 2157.96 3051.58
River Rch & RM=337,43,8495.031
 1030.71 1420.49  1749.9 2160.13 3055.08
River Rch & RM=337,43, 8071.79
 1040.94 1436.67  1770.4 2188.63  3101.2
River Rch & RM=337,43,7347.281
 1054.22  1457.7 1797.07 2225.77 3161.42
River Rch & RM=337,43,6962.345
 1080.22 1498.98 1849.46 2298.92 3280.45
River Rch & RM=337,43, 6620.88
 1085.99 1508.15 1861.11 2315.23 3307.06
River Rch & RM=337,43,6107.863
 1093.85 1520.67    1877 2337.49 3343.42
River Rch & RM=337,43,5474.735
 1118.46 1559.95  1926.9 2407.55  3458.2
River Rch & RM=337,43,5009.621
    1120 1562.41 1930.04 2411.96 3465.44
Boundary for River Rch & Prof#=337,43,1
Up Type= 0
Dn Type= 2
Boundary for River Rch & Prof#=337,43,2
Up Type= 0
Dn Type= 2
Boundary for River Rch & Prof#=337,43,2
Up Type= 0
Dn Type= 2
Boundary for River Rch & Prof#=337,43,2
Up Type= 0
Dn Type= 2
Boundary for River Rch & Prof#=337,43,2
Up Type= 0
Dn Type= 2

--- 337_ras.g01 (geometry) ---

Geom Title=337
Program Version=4.10

River Reach=337,43
Reach XY= 30
1239778.70718411627890.9314597991239811.20713905626672.598487183
1239742.04047937626211.7652926581239394.54055915625430.932201217
1239213.70725838624716.7657518431239337.04054125624233.432558432
1239482.87382917624151.765911745 1239737.8737442623817.599336876
1239947.04033697623399.2661216611239852.87368044 622793.43297091
  1239649.540395622377.599766946 1239671.2070444622004.266543807
1239253.70716191621809.2666138461238982.87390052 621535.10003648
1238837.04060015621189.2668100461238908.70723928620970.100206372
 1238381.2073896620786.7669427981238332.87406105620460.933707614
1238447.88257138620325.8957691341238304.54927268620062.562518153
1238400.38256939619775.8959338231237866.21605588619622.562661543
1237263.71621248618894.2295619541236917.04964256618703.396295378
1236689.54970938618692.5629718731236622.04972683618607.562999072
1236821.21631897618066.729820542 1237818.7160007617245.063368805
1237945.38262425617047.5634237831237868.32122574 617022.55678674

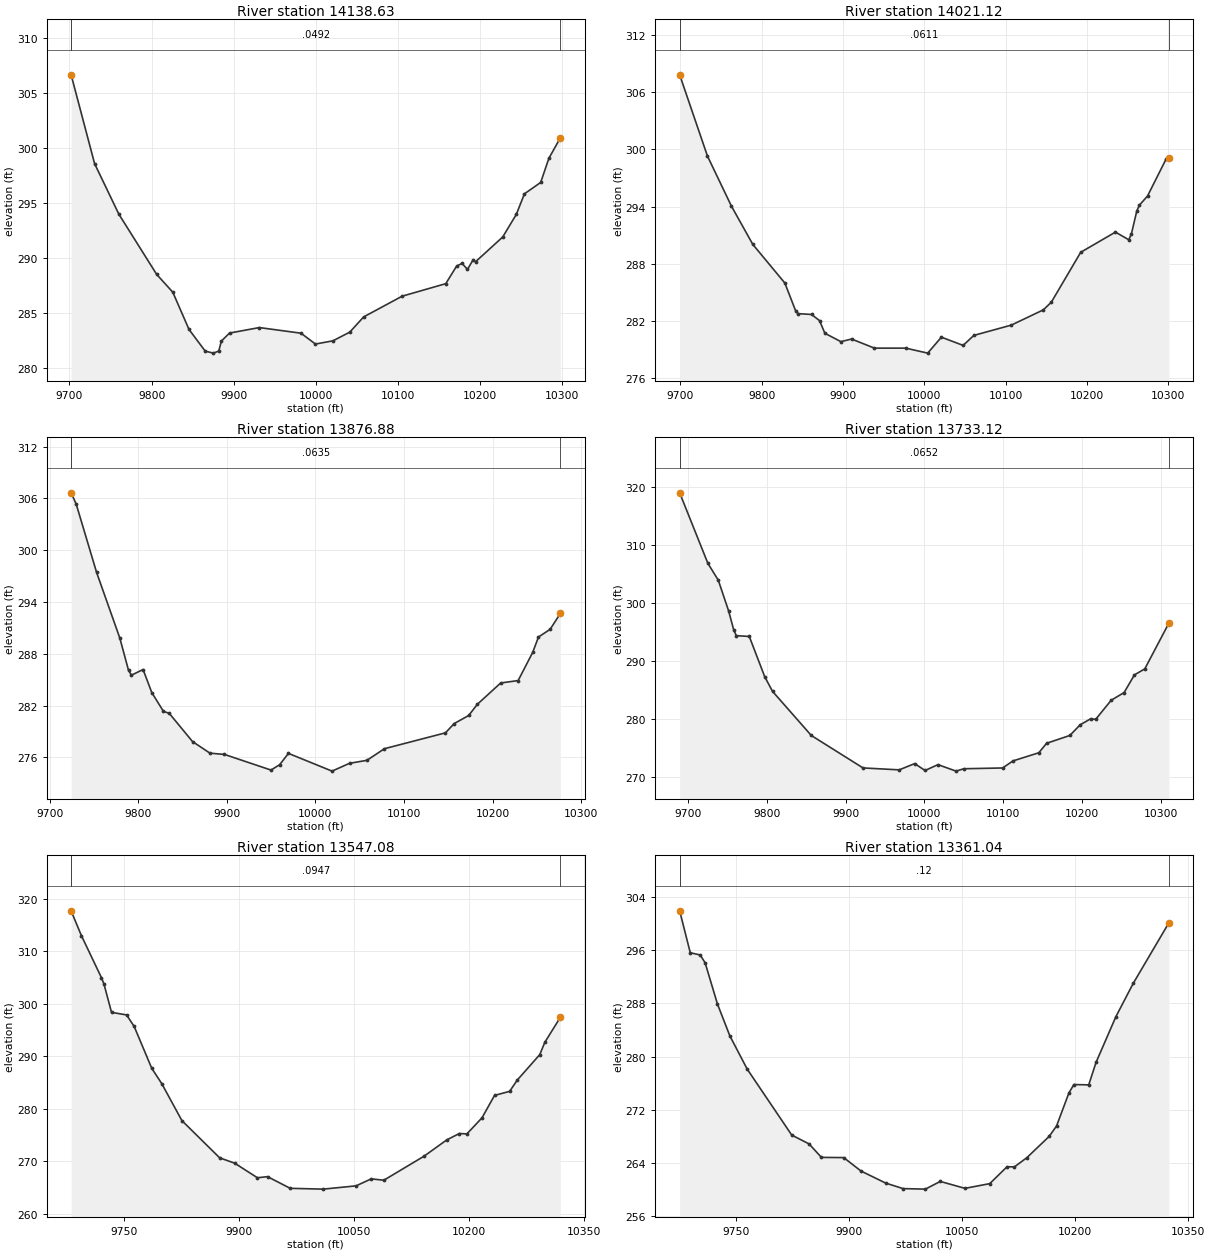
Type RM Length L Ch R = 1 ,14138.63,117.506500,117.506500,117.506500
XS GIS Cut Line= 6
1240072.90474539 627855.496143331239841.75038647627871.962251743
1239804.99854882627879.7243607541239751.69149711627900.736291068
1239702.75522811627912.9330768931239485.80805678627941.983234922
#Sta/Elev= 30
9701.997306.66469730.578 298.5759760.152293.96839806.157  288.499825.874286.8604
 9845.59283.47049865.328281.49649875.222281.31139881.818281.50039885.116282.4163
 9895.01283.13919931.289  283.649982.029 283.1279999.613282.139910020.86282.4299
10041.48283.224310058.39284.611110105.25286.498210158.39287.639310171.66289.2426
10178.26289.484310184.87288.940910191.48289.783610194.78289.640710227.82291.8946
10244.33293.945610254.25295.822810274.07296.863110283.98299.051710298.02300.9311
#Mann= 3 , 0 , 0
9701.997  0.0492       09701.997  0.0492       010298.02  0.0492       0
#XS Ineff= 2 , 0
       0                               0
Bank Sta=9701.997,10298.02
Exp/Cntr=0.3,0.1

Type RM Length L Ch R = 1 ,14021.12,144.242500,144.242500,144.242500
XS GIS Cut Line= 6
1240075.22706529627790.5932443321239862.32484292627791.618110697
1239812.78611014627784.9599625611239739.31348211627767.023740254
1239689.52287734627762.5060440931239476.74730473627770.186046132
#Sta/Elev= 30
9699.224 307.8149733.372299.29799762.907294.03569789.161290.03039828.543285.9807
 9841.67283.09689844.952282.76879861.362282.68579871.208282.03799877.772280.7109
9897.464279.83419910.592280.10849938.669279.15489977.106279.155410004.19278.6304
10021.03280.303110047.76279.441110060.93280.489510106.98281.567610146.35283.1674
10156.19283.969910192.31289.203510235.02291.321710251.45290.515110254.73291.1573
 10261.3293.545510264.59294.159810274.45295.101310297.44299.008410300.77299.0681
#Mann= 3 , 0 , 0
9699.224  0.0611       09699.224  0.0611       010300.77  0.0611       0
#XS Ineff= 2 , 0
       0                               0
Bank Sta=9699.224,10300.77
Exp/Cntr=0.3,0.1

Type RM Length L Ch R = 1 ,13876.88,143.757500,143.757500,143.757500
XS GIS Cut Line= 2
 1240043.5458979627644.9744846521239491.46256453627641.502262414
#Sta/Elev= 30
9724.288306.65129730.026305.34189752.992297.44549779.239 289.8299789.082286.0839
9792.363285.53489805.487286.18899815.329283.51319828.453281.34649835.015281.1124
9861.262 277.8489880.947276.50219897.352276.35269949.846274.54449959.689275.1713
9969.532276.476510018.75 274.42110038.43275.326310058.12275.6725 10077.8277.0165
 10146.7278.854810156.54279.925510172.95280.866410182.79282.170910209.04284.6303
10228.72284.908610245.13288.165210251.69289.953210264.81290.842110276.38 292.681
#Mann= 3 , 0 , 0
9724.288  0.0635       09724.288  0.0635       010276.38  0.0635       0
#XS Ineff= 2 , 0
       0                               0
Bank Sta=9724.288,10276.38
Exp/Cntr=0.3,0.1

Type RM Length L Ch R = 1 ,13733.12,186.039200,186.039200,186.039200
XS GIS Cut Line= 6
 1240090.0825958627505.8851892191239821.05743454627500.343778976
1239778.58577725627502.003209426 1239738.1010699627503.260858204
 1239598.3592899627498.1402721391239469.12195827627496.854145558
#Sta/Elev= 30
 9689.41318.92529725.289306.75719738.415303.88119751.541298.58679758.104295.2739
9761.385294.31729777.793294.18049797.482287.21369807.327284.7183 9856.55277.1201
 9922.18271.53069968.126271.19849987.824272.278110000.96271.088310017.38272.0963
10040.35270.9795 10050.2271.389910099.45271.523310112.58272.737610145.41274.1457
10155.26275.7737 10184.8277.124710197.93278.959910211.05279.982710217.61279.9034
 10237.3283.1924 10253.7284.517710266.83287.563510279.95288.594710310.58296.4909
#Mann= 3 , 0 , 0
 9689.41  0.0652       0 9689.41  0.0652       010310.58  0.0652       0
#XS Ineff= 2 , 0
       0                               0
Bank Sta=9689.41,10310.58
Exp/Cntr=0.3,0.1

Type RM Length L Ch R = 1 ,13547.08,186.039200,186.039200,186.039200
XS GIS Cut Line= 6
1240113.47644726627337.7552413811239881.82199864627328.794014935
  1239825.849374627323.8485261931239740.30797618627312.830891415
1239669.03307819627307.5215601311239476.18093374627302.121393796
#Sta/Elev= 30
9680.649317.68799693.987312.98419720.245304.94589723.528303.73889733.374298.3447
9753.068297.85139762.915295.66899785.891287.6885 9799.02284.74849825.288277.7133
9874.564270.62659894.275269.5988 9923.87266.82739937.045 267.0429966.687264.8157
10009.71264.663210052.69 265.28710072.44266.619510088.89266.3589 10141.5270.9476
10171.05274.044810187.47 275.25910197.32275.182610217.02278.245210233.43282.5241
10253.12283.292410262.96285.419610292.49290.297110299.06292.636510319.35297.4046
#Mann= 3 , 0 , 0
9680.649  0.0947       09680.649  0.0947       010319.35  0.0947       0
#XS Ineff= 2 , 0
       0                               0
Bank Sta=9680.649,10319.35
Exp/Cntr=0.3,0.1

Type RM Length L Ch R = 1 ,13361.04,186.039200,186.039200,186.039200
XS GIS Cut Line= 6
1240114.19008482627141.7417771291239811.69251727627133.696312412
1239790.91243538 627134.160759431239766.23278423627135.057346512
1239604.09481234627131.6958934611239465.57669605627131.987594692
#Sta/Elev= 30
 9675.61301.94669689.662295.6371 9702.79295.30579709.354294.12639725.764287.9023
9742.174283.12219765.147278.12489824.223268.19649847.197266.86679863.607264.8366
9893.145264.80679916.119262.77899948.939260.96529971.913260.138410001.46 260.061
10021.15261.221610053.97260.177210086.79260.888210109.76263.4311 10119.6263.4127
10136.01264.793710165.54267.990610175.39269.562610191.79274.541510198.36275.7994
10218.04275.751110227.88279.167910254.13286.0255 10277.1291.035410324.39300.1513
#Mann= 3 , 0 , 0
 9675.61    0.12       0 9675.61    0.12       010324.39    0.12       0
#XS Ineff= 2 , 0
       0                               0
Bank Sta=9675.61,10324.39
Exp/Cntr=0.3,0.1

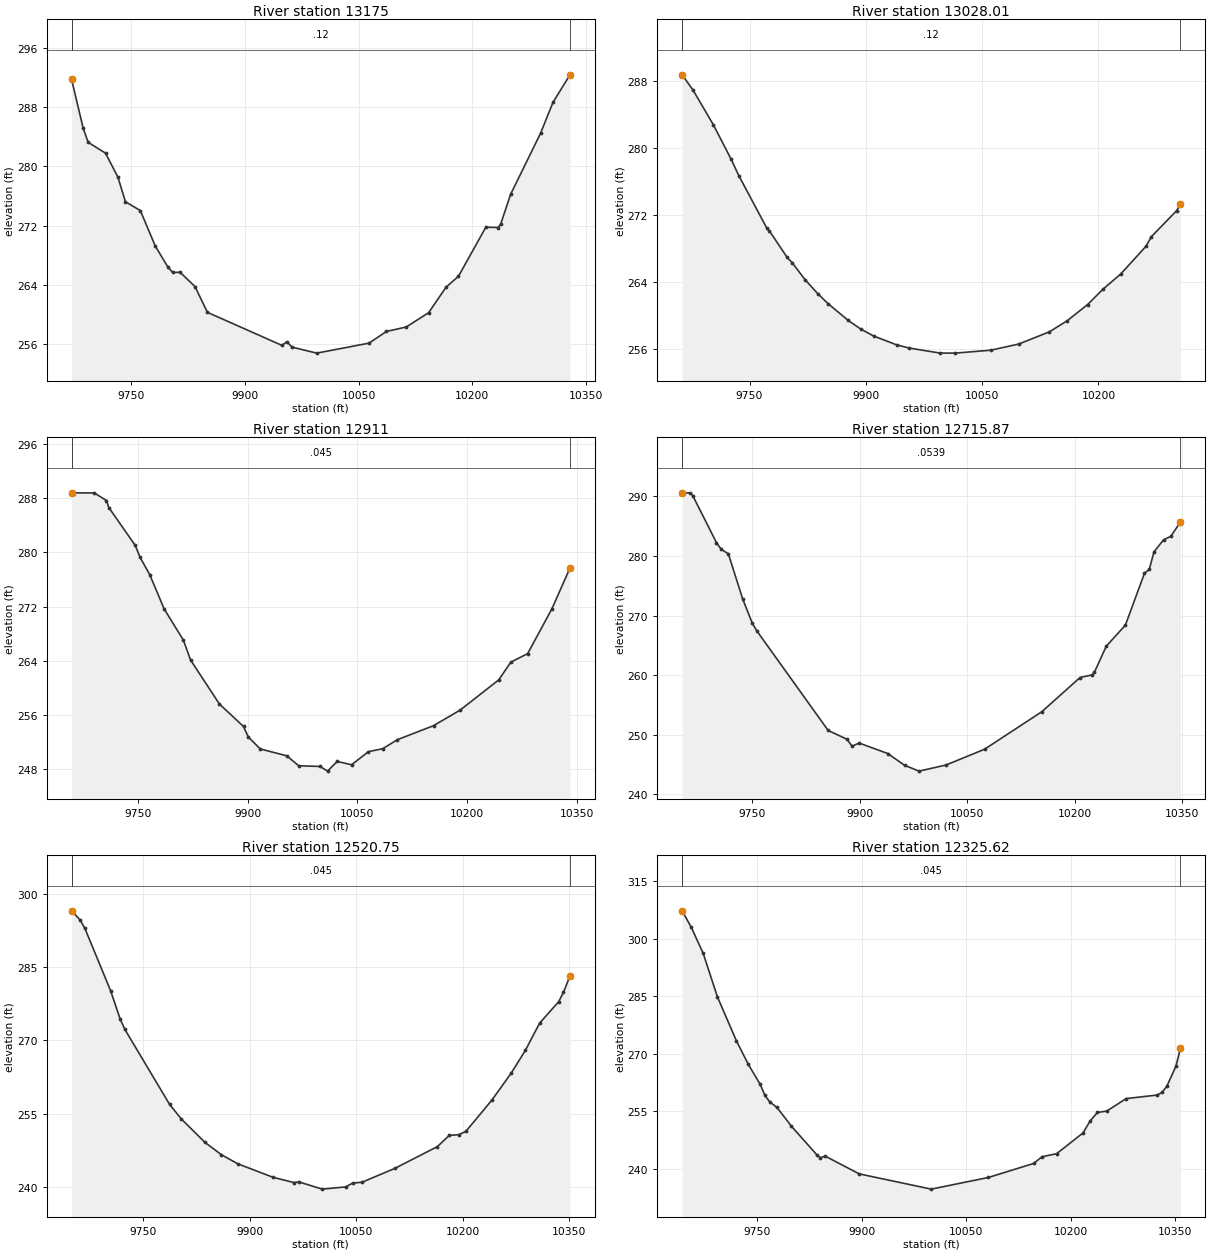
Type RM Length L Ch R = 1 ,   13175,146.991100,146.991100,146.991100
XS GIS Cut Line= 6
 1240125.2977401626946.2476166811239884.10778624626946.517470738
 1239797.3216409   626949.921062 1239795.3240162626950.018507166
1239723.60208478626953.2402906241239467.44476529626960.115261152
#Sta/Elev= 30
9670.957291.75149686.269285.1528 9692.83283.24939715.796281.7854  9732.2 278.519
9742.043275.22379761.728274.02539781.413269.23939797.817266.44329804.379 265.657
9814.221265.68429833.906263.7511 9850.31260.26639948.764255.7982 9955.33256.3019
9961.897255.56619994.731254.7527 10063.7256.102910086.68257.681110112.93258.2871
10142.47 260.22310165.45263.670710181.86265.141410217.96271.776510234.37271.7349
10237.65272.224410250.78276.238310290.16284.460110306.57288.640910329.04292.3738
#Mann= 3 , 0 , 0
9670.957    0.12       09670.957    0.12       010329.04    0.12       0
#XS Ineff= 2 , 0
       0                               0
Bank Sta=9670.957,10329.04
Exp/Cntr=0.3,0.1

Type RM Length L Ch R = 1 ,13028.01,117.008900,117.008900,117.008900
XS GIS Cut Line= 3
1240133.82367566626815.1133735481239647.71256453626797.752262428
1239491.46256453626797.752262428
#Sta/Elev= 30
 9663.11288.77139677.114286.95299703.378282.79869726.358278.66539736.207276.7096
9772.319270.43399775.602270.12019798.582266.92489805.148266.28779821.563 264.277
9837.977262.60089851.109261.41829877.373259.39169893.787258.34419910.202257.5308
9939.748256.47469956.163256.08929995.558255.495410015.26255.486310061.22255.8364
10097.33256.578610136.72258.0332 10159.7259.360310185.94261.294110205.63263.1168
 10228.6264.9419 10261.4268.274510267.97269.390710300.77272.519810305.78273.3112
#Mann= 3 , 0 , 0
 9663.11    0.12       0 9663.11    0.12       010305.78    0.12       0
#XS Ineff= 2 , 0
       0                               0
Bank Sta=9663.11,10305.78
Exp/Cntr=0.3,0.1

Type RM Length L Ch R = 1 ,   12911,195.127600,195.127600,195.127600
XS GIS Cut Line= 6
1240150.91686851626672.9750800481239905.53864727626686.693218546
1239809.87729871626687.1001183941239750.56828504626687.902035858
1239656.93946067626696.0699819241239471.85056847626715.652973028
#Sta/Elev= 30
9659.576  288.799690.712288.77099707.142287.65539710.428286.62379746.574281.0229
9753.146279.26039766.289 276.7289786.005271.66089812.293267.05119822.151264.1082
9861.582257.61579894.442254.30269901.014252.74219917.425250.98429953.514249.9763
9969.919248.5036    9999248.403410009.29 247.71410022.41249.1468 10042.1248.6517
10065.09250.584510084.85251.034210104.61 252.35110154.01254.4216 10190.3256.7146
10243.13261.179810259.58263.792810282.67 265.06210315.66271.645610340.42 277.684
#Mann= 3 , 0 , 0
9659.576   0.045       09659.576   0.045       010340.42   0.045       0
#XS Ineff= 2 , 0
       0                               0
Bank Sta=9659.576,10340.42
Exp/Cntr=0.3,0.1

Type RM Length L Ch R = 1 ,12715.87,195.127500,195.127500,195.127500
XS GIS Cut Line= 6
1240101.68180219626448.3793449431239823.35232559626487.890305236
1239784.01177786626495.6111350321239738.09458141626509.378091558
1239694.66016969626518.8845546611239417.45156808 626565.67285239
#Sta/Elev= 30
9652.622290.52459664.102 290.5939667.411 290.1229700.505282.23579707.123 281.122
9717.052280.36579736.908272.83319750.145268.79789756.764267.4306  9856.2250.7314
9882.754249.23579889.392248.0865 9899.35248.6201 9939.22246.86589962.624244.8946
 9982.88243.908810020.58244.938510074.27247.582310154.12253.879910207.35259.6125
10223.99260.051910227.32 260.48810243.95264.872610270.57268.401910297.19277.0989
10303.84277.7625 10310.5280.709710323.81282.708210333.79283.297510347.38285.6883
#Mann= 3 , 0 , 0
9652.622  0.0539       09652.622  0.0539       010347.38  0.0539       0
#XS Ineff= 2 , 0
       0                               0
Bank Sta=9652.622,10347.38
Exp/Cntr=0.3,0.1

Type RM Length L Ch R = 1 ,12520.75,195.127600,195.127600,195.127600
XS GIS Cut Line= 6
1240089.06652605626263.7655270281239887.60319882626294.701532634
  1239686.617094626316.7793280191239614.03764569626326.619570533
1239517.53186371626344.3765804381239395.72615944 626371.40441515
#Sta/Elev= 30
9648.919  296.549660.947294.66599667.585292.97789704.098280.10669717.375 274.379
9724.013272.2549 9787.08256.89279803.676253.90859836.869249.13349860.064246.6086
9883.173 244.7429932.692241.99229962.403240.89949969.006 241.05210002.01239.5656
   10035240.0172 10044.9240.797910058.11240.978910104.46243.816510164.33248.2753
10181.01250.561910194.35250.716410204.36251.368410241.16257.809110268.05263.2551
10288.21267.955910308.37273.557710335.26277.948710341.98279.873210351.08283.1879
#Mann= 3 , 0 , 0
9648.919   0.045       09648.919   0.045       010351.08   0.045       0
#XS Ineff= 2 , 0
       0                               0
Bank Sta=9648.919,10351.08
Exp/Cntr=0.3,0.1

Type RM Length L Ch R = 1 ,12325.62,159.728400,159.728400,159.728400
XS GIS Cut Line= 6
1240037.33996097626003.170618155 1239815.4644562626071.162007003
1239746.13842441626100.5433136331239670.93937622626145.897971262
1239625.71926187626167.2395452151239369.61094389626251.345743923
#Sta/Elev= 30
 9642.53307.2114 9655.68 302.9029672.726296.14229693.181284.77629720.453  273.31
9737.499267.19839754.544261.97499761.363259.0876 9768.26257.40539778.633255.9663
9799.378251.06489836.408243.49599840.869242.86219847.784243.28799896.612238.6572
9999.893234.687810082.01237.733510146.78241.378910158.87243.134310179.77243.9203
10217.68249.333610227.99 252.501 10238.3254.668510251.74255.032210279.54258.2834
10324.22259.2111 10331.1 259.90210337.97261.540310350.85266.699310357.45271.3903
#Mann= 3 , 0 , 0
 9642.53   0.045       0 9642.53   0.045       010357.45   0.045       0
#XS Ineff= 2 , 0
       0                               0
Bank Sta=9642.53,10357.45
Exp/Cntr=0.3,0.1

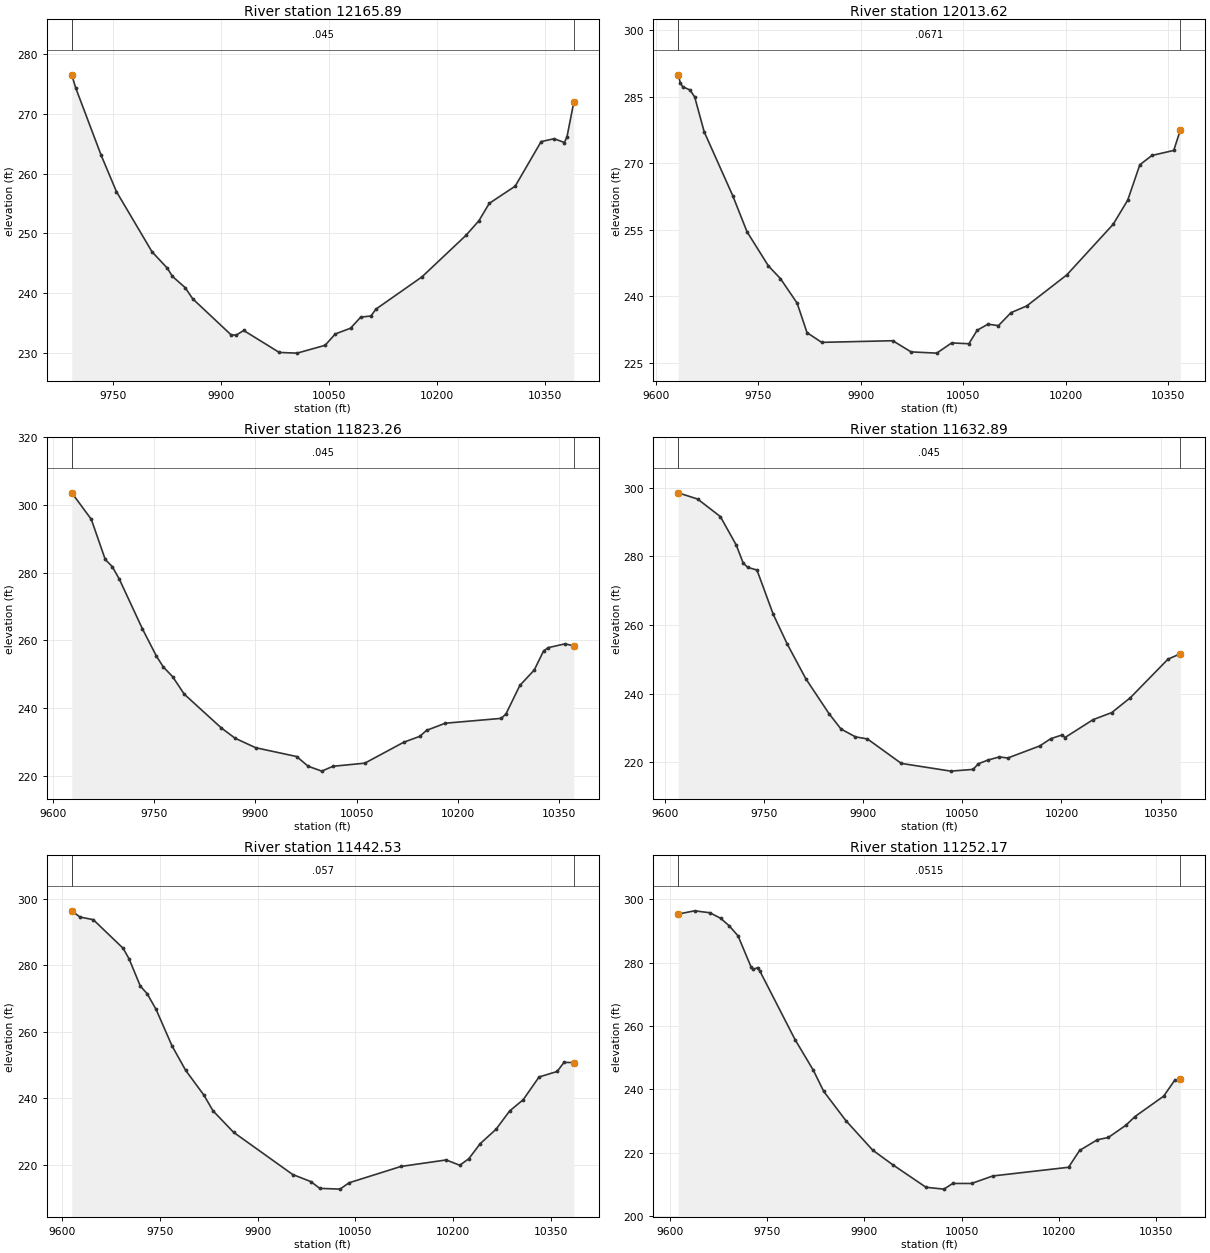
Type RM Length L Ch R = 1 ,12165.89,152.271600,152.271600,152.271600
XS GIS Cut Line= 3
1239931.36223736625865.151768312 1239487.8818354626040.995618448
1239287.70738959  626130.5764478
#Sta/Elev= 30
9693.382276.52219698.871274.32269734.164263.0488 9755.34256.96589804.751246.8813
9825.927244.14889832.985242.77929850.632240.8946 9861.22239.0084 9914.16233.0068
9921.219232.91729931.807233.71819981.217230.037810005.92229.922910044.75231.2318
10058.86233.132310080.04234.094810094.16235.950510108.27236.141910115.33237.2976
10179.01242.682410240.12249.641510258.09252.092610272.47255.003310308.41257.8805
10344.36265.337310362.33265.821810376.71265.1902 10380.3266.165810389.76271.9942
#Mann= 3 , 0 , 0
9693.382   0.045       09693.382   0.045       010389.76   0.045       0
#XS Ineff= 2 , 0
       0                               0
Bank Sta=9693.382,10389.76
Exp/Cntr=0.3,0.1

Type RM Length L Ch R = 1 ,12013.62,190.362600,190.362600,190.362600
XS GIS Cut Line= 6
1239896.42242211625694.2569643041239662.68132904625784.985544437
1239605.14279533625818.3710486061239532.82182221625880.773465602
1239473.71950674 625919.764219071239244.79744109626022.392148027
#Sta/Elev= 30
9632.519 289.9669635.674288.07949639.158287.26719649.609286.56159656.576284.9904
 9670.51 277.1129712.313262.69999733.214254.56489764.567246.84949782.065244.0108
9806.562238.46849821.036231.80719842.504 229.6149946.563229.9845 9973.31227.4652
10010.95227.185910032.79229.491410057.96229.304410070.12232.343810085.89233.7143
10101.27233.389510119.67236.320310142.63237.824910201.27244.828610269.18256.2479
10290.47261.6989 10308.2269.6768 10325.9271.773310357.86 272.91410367.47277.4935
#Mann= 3 , 0 , 0
9632.519  0.0671       09632.519  0.0671       010367.47  0.0671       0
#XS Ineff= 2 , 0
       0                               0
Bank Sta=9632.519,10367.47
Exp/Cntr=0.3,0.1

Type RM Length L Ch R = 1 ,11823.26,190.362700,190.362700,190.362700
XS GIS Cut Line= 6
1239871.80797347625573.2941193251239627.88161827  625649.5688756
1239429.75345232625695.5333021171239368.55260579 625711.86592139
1239286.91341423625738.4165646231239159.06348287625784.297865047
#Sta/Elev= 30
9627.996 303.631 9656.94295.79759677.607 283.937 9687.94281.83559698.273278.1964
9732.717263.41549753.383255.37829763.717252.14849777.494249.28419794.716244.1086
9849.568234.14719870.089231.08459900.623228.28229961.307225.67949978.164 222.829
9998.392221.367710015.19222.8037 10062.3223.7247 10119.8229.899710143.57 231.642
10153.81233.419710181.41235.5278 10264.5236.963910271.47 238.29310291.94246.6884
 10313.3251.248610327.24256.929110334.21257.872410358.61258.9799   10372258.4249
#Mann= 3 , 0 , 0
9627.996   0.045       09627.996   0.045       0   10372   0.045       0
#XS Ineff= 2 , 0
       0                               0
Bank Sta=9627.996,10372
Exp/Cntr=0.3,0.1

Type RM Length L Ch R = 1 ,11632.89,190.362600,190.362600,190.362600
XS GIS Cut Line= 6
 1239809.7982066625351.7085223881239708.70629553625384.035617189
1239597.88666324625426.6214962841239512.40249456625466.999547427
1239328.92246557625566.0517193491239114.13372108625652.356260582
#Sta/Elev= 30
9620.271298.49489649.558296.68939684.003291.57199708.114283.24329718.448278.0675
9725.337276.78329739.374275.98989763.977263.09279785.065254.46589813.183244.3434
9848.434234.12159866.461229.66779888.347227.37639906.489226.76779957.696219.6416
10032.55217.390110066.44 217.89710074.01219.513710089.15220.638910106.13 221.535
10118.66221.209110167.24224.739710183.91226.860510201.52227.965510205.09227.1586
10247.91232.400410276.03234.447410304.12238.776510361.12250.020610379.76251.5966
#Mann= 3 , 0 , 0
9620.271   0.045       09620.271   0.045       010379.76   0.045       0
#XS Ineff= 2 , 0
       0                               0
Bank Sta=9620.271,10379.76
Exp/Cntr=0.3,0.1

Type RM Length L Ch R = 1 ,11442.53,190.362600,190.362600,190.362600
XS GIS Cut Line= 6
1239731.58464476625213.125457493 1239679.4660832 625228.01460516
1239601.42486086625253.3016804261239424.59147759625318.625908717
1239276.95150464625367.4063955841239003.16280086625462.809472185
#Sta/Elev= 30
9614.913  296.339627.412294.47199647.884293.67669693.734285.07929702.836281.9103
 9720.08273.73139730.426271.48389744.221  266.759768.606255.82179789.591248.4536
9817.572241.00749831.562236.2958 9863.04229.85389953.821217.1615  9981.5215.0473
 9995.34213.007610026.42212.773910040.23 214.67210119.79219.579510189.28221.5334
10210.12 219.94210224.02221.915210241.39226.414710265.71230.750810286.56236.2341
 10307.4239.622910331.72246.441210359.52248.098810369.94250.828910385.09250.7625
#Mann= 3 , 0 , 0
9614.913   0.057       09614.913   0.057       010385.09   0.057       0
#XS Ineff= 2 , 0
       0                               0
Bank Sta=9614.913,10385.09
Exp/Cntr=0.3,0.1

Type RM Length L Ch R = 1 ,11252.17,190.362700,190.362700,190.362700
XS GIS Cut Line= 6
1239681.85816125625055.9224790911239570.45886693625079.865905756
1239470.62131295625106.5640332371239308.90818251625156.613889622
1239117.17289298625217.0158346441238936.92462736625268.893809462
#Sta/Elev= 30
 9612.43295.28829637.619296.3024 9661.11295.70569677.888293.96039691.311291.5405
9704.734 288.4269724.869278.60029728.247277.81729735.039278.40079738.435277.3201
9792.773255.69449821.224 245.9549837.004239.37519871.348230.1139 9912.56220.8502
9943.469216.24439994.985209.114510022.51208.530610036.27210.315110065.25210.3192
10098.18212.686810215.01215.418610232.08220.724510259.39224.096710276.46224.8207
10303.78228.705710317.43231.394110361.81237.837410378.89242.843910387.59243.1692
#Mann= 3 , 0 , 0
 9612.43  0.0515       0 9612.43  0.0515       010387.59  0.0515       0
#XS Ineff= 2 , 0
       0                               0
Bank Sta=9612.43,10387.59
Exp/Cntr=0.3,0.1

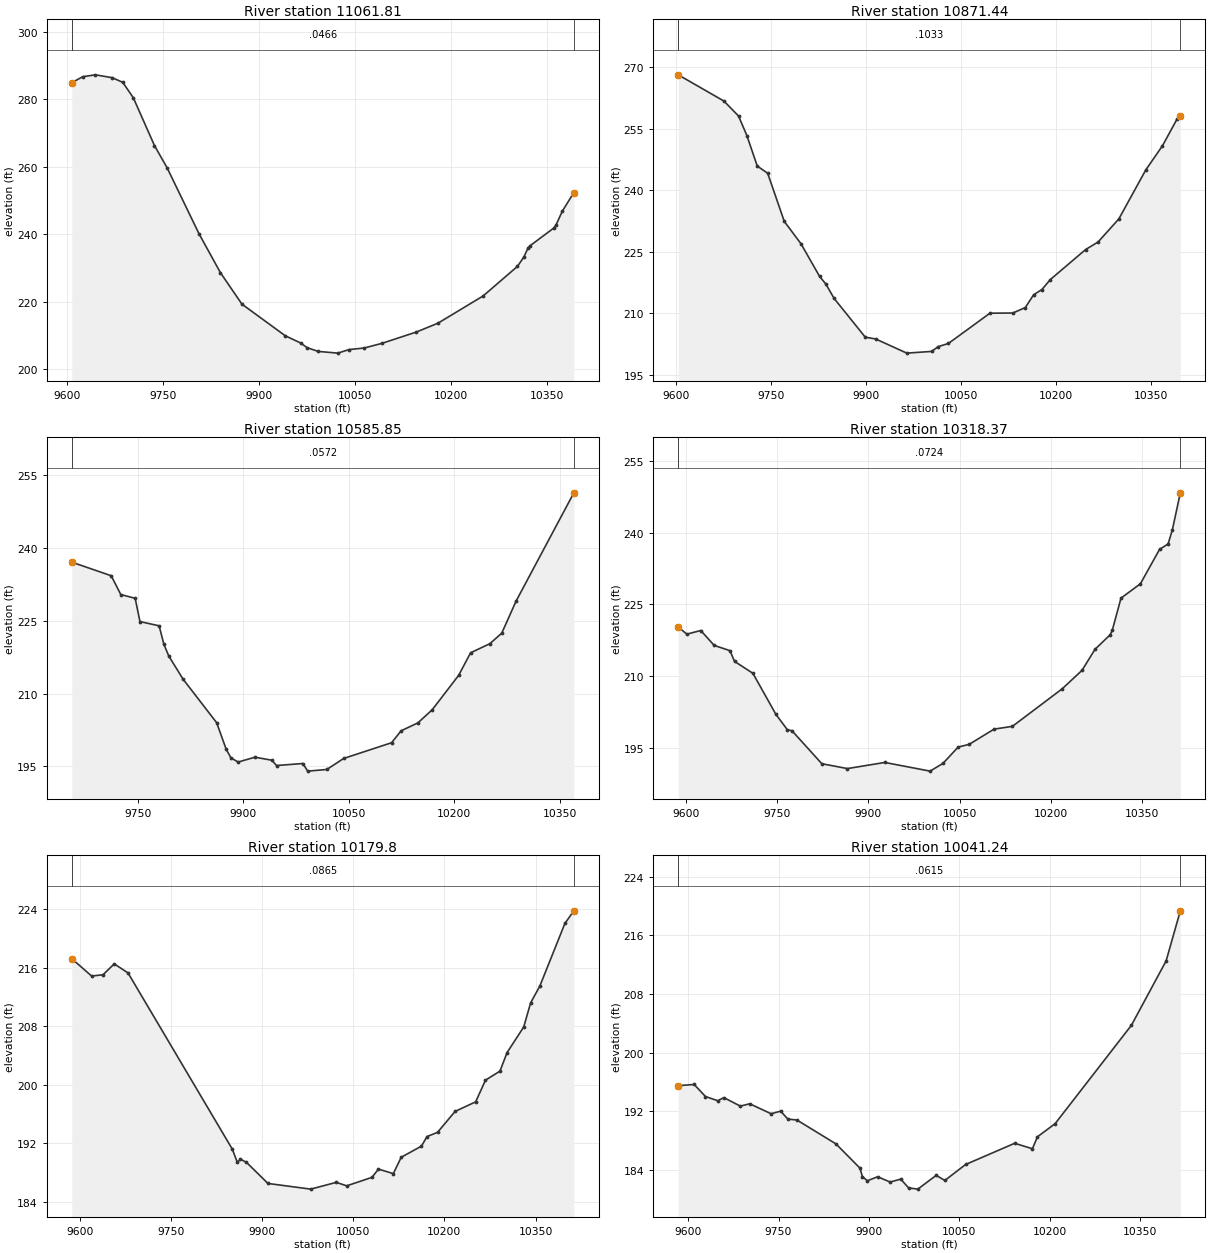
Type RM Length L Ch R = 1 ,11061.81,190.362600,190.362600,190.362600
XS GIS Cut Line= 6
1239634.89567588624905.8362354641239516.78139912624916.909217447
1239385.90604596624938.8007435761239313.38696558624956.425496395
1239106.63503259625016.1179294111238868.63855817625066.541363881
#Sta/Elev= 30
9607.752284.89389624.861286.66139644.633287.22429670.994286.3779 9687.47284.9923
9703.947280.41349736.963266.26939756.856259.63059806.678 240.0999840.073228.5952
9873.627 219.2889941.267209.92559965.262 207.7829975.545206.38489992.684205.2856
10023.59204.771410040.75205.819610064.73206.292410091.88207.636910146.18211.0215
10179.86213.631610250.52221.707410304.07230.459110314.11 233.223 10320.8235.9571
10324.15236.627410360.95241.834310364.29242.677610374.33246.856810392.27252.3383
#Mann= 3 , 0 , 0
9607.752  0.0466       09607.752  0.0466       010392.27  0.0466       0
#XS Ineff= 2 , 0
       0                               0
Bank Sta=9607.752,10392.27
Exp/Cntr=0.3,0.1

Type RM Length L Ch R = 1 ,10871.44,285.591500,285.591500,285.591500
XS GIS Cut Line= 6
1239614.63929884624794.2153434631239444.49012223624786.202443649
1239324.29595597624785.1136896241239222.05239207624788.574468227
1239217.24741622624788.7994917581238822.03349922624807.714437431
#Sta/Elev= 30
9603.351268.10649675.668261.6969 9698.66258.05199711.797 253.293 9728.22245.8479
9744.642244.10549770.918232.35329797.169226.93129826.697218.9383 9836.54217.0839
9849.664213.56289898.881 204.1169915.295203.67719964.535200.223110003.93200.6418
10013.76201.788510030.21 202.577 10095.9209.965910132.03210.007610151.74211.3343
10164.88214.455910178.02215.741110191.15218.151410246.99225.4853 10266.7 227.325
10299.55232.962110342.24244.945110368.52250.809610391.51257.321510396.67 258.012
#Mann= 3 , 0 , 0
9603.351  0.1033       09603.351  0.1033       010396.67  0.1033       0
#XS Ineff= 2 , 0
       0                               0
Bank Sta=9603.351,10396.67
Exp/Cntr=0.3,0.1

Type RM Length L Ch R = 1 ,10585.85,267.478900,267.478900,267.478900
XS GIS Cut Line= 2
1239609.51812011624610.2522624281238922.01812011624415.807817981
#Sta/Elev= 30
9655.815237.06219711.926234.26899725.564230.39799746.021229.6231 9752.84224.8325
9780.116223.95669786.935220.13859793.755217.76359814.212212.97129861.945 204.017
9875.583198.53819882.402196.75189892.631 195.9099916.498196.90439940.364196.2881
9947.183195.19199984.688 195.6069991.507194.037310018.78194.374210042.65 196.643
10110.84199.881610124.48202.339510148.35203.9688 10168.8206.683310206.31213.7506
10223.36218.405710250.63220.262910267.68222.440710288.14 229.06210370.28251.3381
#Mann= 3 , 0 , 0
9655.815  0.0572       09655.815  0.0572       010370.28  0.0572       0
#XS Ineff= 2 , 0
       0                               0
Bank Sta=9655.815,10370.28
Exp/Cntr=0.3,0.1

Type RM Length L Ch R = 1 ,10318.37,138.568200,138.568200,138.568200
XS GIS Cut Line= 6
1239683.58104923624461.1548219611239527.02381014624376.731613164
1239353.74193978624266.1877399761239283.10548125624237.688429312
1239094.53703021624148.2481725761238949.46381747 624091.05748432
#Sta/Elev= 30
9587.833220.27169601.881218.7476 9624.79219.51159646.895216.39279672.734215.2972
9680.269213.05659710.408210.55759748.082     2029766.944198.76939774.639198.5423
9823.623191.64949865.598190.63579926.991191.9153 10001.4190.101210022.63191.7356
10047.39195.122510065.62195.707310106.45198.886410136.54 199.468 10218.3207.3216
10250.78211.176110272.17215.585510297.03218.619310300.58219.598910314.79226.2801
10346.66229.287410378.15236.483410392.15237.611210399.15240.573410412.19248.3059
#Mann= 3 , 0 , 0
9587.833  0.0724       09587.833  0.0724       010412.19  0.0724       0
#XS Ineff= 2 , 0
       0                               0
Bank Sta=9587.833,10412.19
Exp/Cntr=0.3,0.1

Type RM Length L Ch R = 1 , 10179.8,138.568100,138.568100,138.568100
XS GIS Cut Line= 6
1239761.51534723624434.2018585241239555.33288441624306.635446222
1239489.23853929624245.2432490381239320.91012083624050.027651366
1239241.88003304623988.7758220021239126.05422619623919.848155785
#Sta/Elev= 30
9586.927217.23649619.624214.86449638.232215.03839656.839 216.524 9679.45215.2941
9851.011191.19019859.425189.36259864.497189.81539874.397189.37449909.788186.4865
9980.147185.711810022.15186.6385 10039.3186.162810080.87187.318210091.55188.4529
10116.02187.832910129.05190.073110162.38191.595410171.39192.899710188.75193.4791
10217.69196.344410251.49197.650310267.69200.618610291.51201.853610303.23 204.399
10330.58207.894410341.97211.195610357.01 213.47410398.39222.066910413.07223.7856
#Mann= 3 , 0 , 0
9586.927  0.0865       09586.927  0.0865       010413.07  0.0865       0
#XS Ineff= 2 , 0
       0                               0
Bank Sta=9586.927,10413.07
Exp/Cntr=0.3,0.1

Type RM Length L Ch R = 1 ,10041.24,133.621200,133.621200,133.621200
XS GIS Cut Line= 6
1239870.17889709624326.9944246231239708.51117364624225.430478593
1239606.37462707 624146.872800261239374.19559376623953.546338994
1239297.71976576623899.5471310371239197.07576506623840.077127806
#Sta/Elev= 30
9583.719195.5124 9610.18195.66859628.911194.02839649.327193.45279659.276193.8818
9686.777192.72059702.236193.04149737.755191.68129753.542192.03659765.382190.9571
9780.648190.81989845.224187.57379884.958184.27679889.097183.12499897.375182.5366
9914.282183.09219935.035182.37319952.797182.76679965.636181.57159981.023181.4034
10011.51 183.28210025.79182.587510060.33184.763910141.64187.654310171.03186.9104
10179.42188.538310208.68190.327310335.23203.7453 10392.8 212.525 10416.3219.3455
#Mann= 3 , 0 , 0
9583.719  0.0615       09583.719  0.0615       0 10416.3  0.0615       0
#XS Ineff= 2 , 0
       09916.434        10085.37       0
Bank Sta=9583.719,10416.3
Exp/Cntr=0.3,0.1

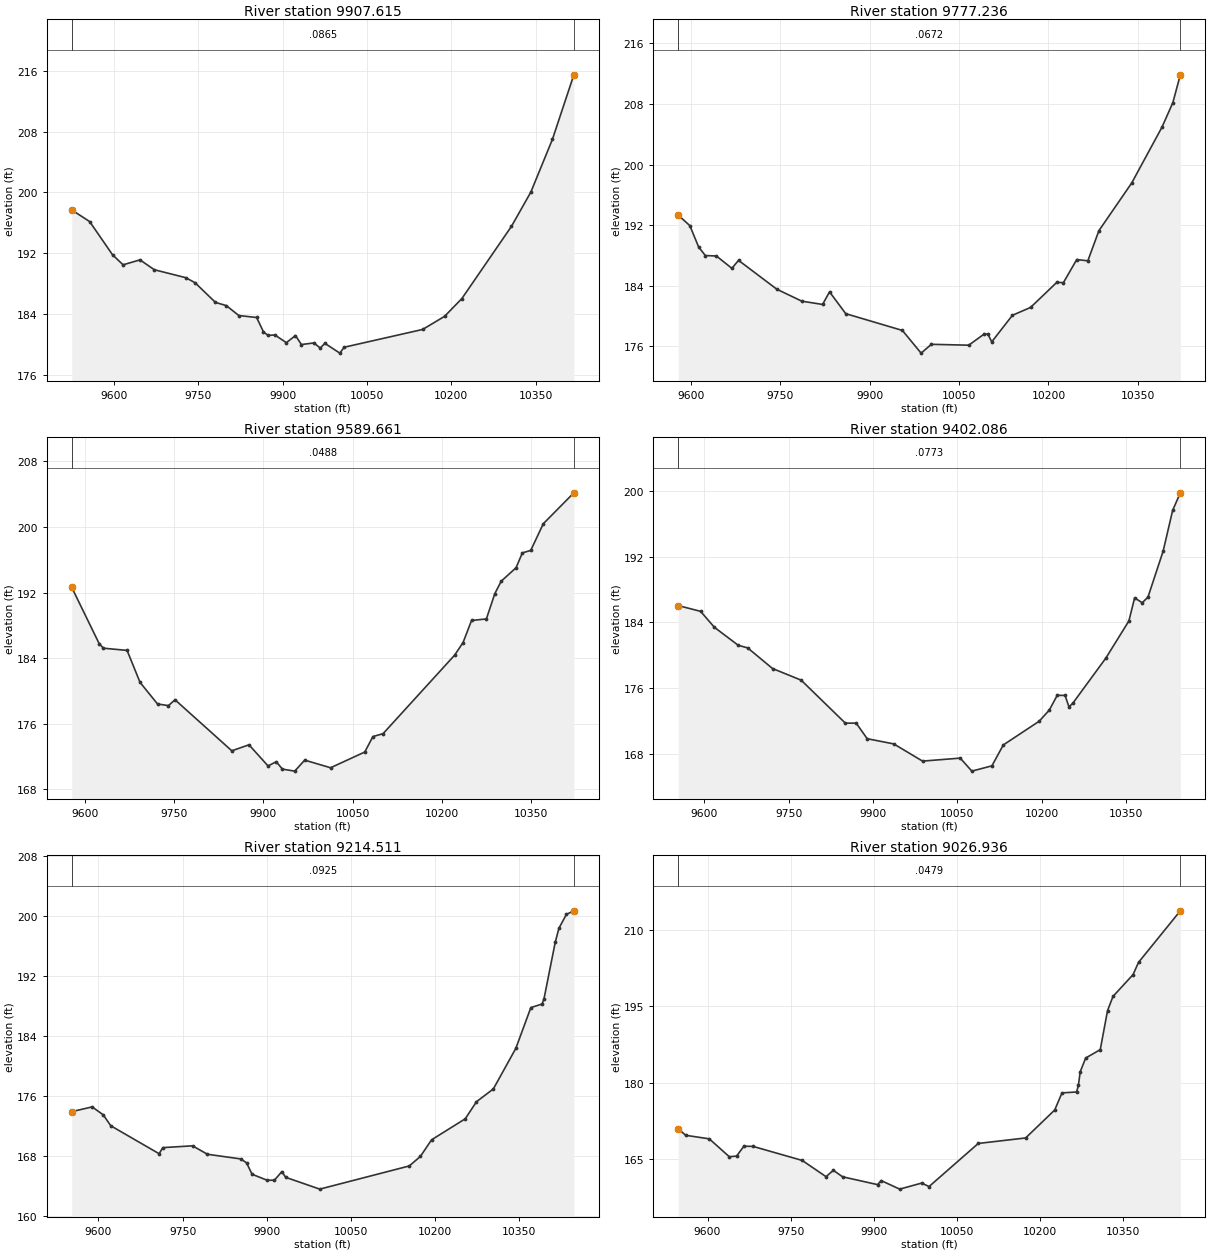
Type RM Length L Ch R = 1 ,9907.615,130.378800,130.378800,130.378800
XS GIS Cut Line= 4
1239997.86447427624255.9437020721239642.47084445623996.153036997
1239447.10826436623881.8451443611239253.82400954623765.458926424
#Sta/Elev= 30
9525.493  197.689557.294196.14959597.934 191.7749616.664190.45369646.701191.1039
9672.259189.80369727.853188.76319744.532188.09629780.811185.49979800.127185.0796
9822.364183.77019853.961183.51359866.153181.62279874.281181.15269886.473181.2117
9906.793180.19559923.048181.13669933.554179.95029955.791180.15999967.112179.4896
9975.222180.110610001.83178.818410009.43179.591310149.01181.937910188.09183.6708
 10218.7186.009210306.78195.515510341.25200.031910379.54206.968110417.68215.4821
#Mann= 3 , 0 , 0
9525.493  0.0865       09525.493  0.0865       010417.68  0.0865       0
#XS Ineff= 2 , 0
       09913.662        10049.21       0
Bank Sta=9525.493,10417.68
Exp/Cntr=0.3,0.1

Type RM Length L Ch R = 1 ,9777.236,187.575000,187.575000,187.575000
XS GIS Cut Line= 6
  1240051.712273624093.2560470771239870.40392338623992.439661228
1239710.12299416623886.3264791321239570.81107019623802.558077408
1239429.83671994623726.9191584271239321.17082505623674.612495799
#Sta/Elev= 30
9578.524193.31069597.991191.92429612.857189.08889624.006187.97059642.588187.9119
9668.603186.28159679.753 187.3379744.102183.51799785.925 181.9449820.883181.5067
9832.536183.17569859.727180.29079954.874178.07319986.272175.075610003.56176.2404
10066.24176.124210092.33177.606510098.56177.576110104.83176.561210139.56180.0725
10170.07181.116310214.08184.424610225.24184.393310247.58187.4416 10266.2187.2735
10284.82191.262610339.79197.548610390.76204.946310408.97208.179510421.46211.8502
#Mann= 3 , 0 , 0
9578.524  0.0672       09578.524  0.0672       010421.46  0.0672       0
#XS Ineff= 2 , 0
       0                               0
Bank Sta=9578.524,10421.46
Exp/Cntr=0.3,0.1

Type RM Length L Ch R = 1 ,9589.661,187.575000,187.575000,187.575000
XS GIS Cut Line= 6
1240135.37360335623876.2414995221239846.93486577623736.795988339
1239797.73618808623720.3087472461239708.26543285623702.077127784
1239646.70031491623683.6784468281239353.45471713623563.974579245
#Sta/Elev= 30
9577.677192.63079623.734185.78539630.965185.22399670.737184.95629692.509181.0628
9721.926178.42629740.312178.22389751.344178.93949846.933172.71579875.808173.4483
9907.872170.87169921.712171.38219932.093170.48259952.766 170.2399969.538171.5807
10013.07170.650210070.61 172.56910084.31174.452710101.43174.8091 10221.7184.3712
10235.96185.912510250.23 188.60410275.19188.793710289.45191.885410300.15193.3916
10325.11195.032610335.73196.842910349.82197.144210370.95200.398710422.34204.1639
#Mann= 3 , 0 , 0
9577.677  0.0488       09577.677  0.0488       010422.34  0.0488       0
#XS Ineff= 2 , 0
       0                               0
Bank Sta=9577.677,10422.34
Exp/Cntr=0.3,0.1

Type RM Length L Ch R = 1 ,9402.086,187.574900,187.574900,187.574900
XS GIS Cut Line= 6
1240242.29168443623807.9795207191239942.31137736623666.929621169
1239887.49303062623618.3583384471239818.92714874623520.106706506
 1239749.2785044623468.9192816981239483.20072665623383.253297428
#Sta/Elev= 30
9553.633186.05149593.387185.34839617.955183.40449660.462181.20679677.094180.8982
9721.272178.38539772.179176.96679850.768171.72869870.039171.73429889.573169.8359
9936.859169.2005 9987.99167.104710055.03167.469610075.68165.884510111.37166.5299
10131.63169.074310195.26171.956710213.35 173.31510227.49 175.12110241.42175.1053
10248.38 173.70710255.34174.169410313.97179.657510354.88184.1753 10365.1186.9838
10378.72186.397810388.84 187.08910415.82192.689110432.69197.646910446.33 199.787
#Mann= 3 , 0 , 0
9553.633  0.0773       09553.633  0.0773       010446.33  0.0773       0
#XS Ineff= 2 , 0
       0                               0
Bank Sta=9553.633,10446.33
Exp/Cntr=0.3,0.1

Type RM Length L Ch R = 1 ,9214.511,187.575000,187.575000,187.575000
XS GIS Cut Line= 6
1240382.15871954623490.6578503341240017.86964354623437.930473175
1239896.70065027623407.8113684621239801.61572279623401.406297121
1239737.40288152623392.6584579971239499.92253659623347.144948196
#Sta/Elev= 30
9552.486173.91599588.813 174.5499608.704173.48269621.964172.03479708.154168.3036
9714.784169.11469767.825169.35559794.345168.22859853.428167.6107 9863.96167.0965
9873.905165.56449900.425164.77189913.686164.76779927.006165.92259933.698165.1579
 9994.53163.579310154.14166.6715   10174167.949710193.87170.159510253.89172.9611
10273.94175.2403   10304176.946310344.09182.361910370.81187.791810390.86188.2727
 10394.2188.944910414.24196.484710420.92198.392410434.28 200.23510447.47 200.702
#Mann= 3 , 0 , 0
9552.486  0.0925       09552.486  0.0925       010447.47  0.0925       0
#XS Ineff= 2 , 0
       0                               0
Bank Sta=9552.486,10447.47
Exp/Cntr=0.3,0.1

Type RM Length L Ch R = 1 ,9026.936,102.835200,102.835200,102.835200
XS GIS Cut Line= 6
1240336.55238459623210.1785210691240111.76473652623222.185059871
1239912.52482328623252.1690052531239758.60692151623263.530123338
1239637.97861157623263.8986245771239434.34383031623251.429411421
#Sta/Elev= 30
 9547.16171.01059560.481169.7088 9603.16169.01429639.273165.51049652.405165.6294
9665.541 167.5649681.987167.53729770.797 164.783 9813.76161.60269826.982162.8522
9843.509161.58039906.651160.04519913.308 160.8349946.593159.16059986.396160.3497
9999.562159.662510088.38168.1096 10173.8169.1867 10226.3174.667810239.43178.0177
10265.71178.192210268.99179.477910272.28182.160110282.14184.847810308.44186.4903
10321.58194.135810331.45196.9248 10367.6201.191710377.46203.590910452.85 213.689
#Mann= 3 , 0 , 0
 9547.16  0.0479       0 9547.16  0.0479       010452.85  0.0479       0
#XS Ineff= 2 , 0
       0                               0
Bank Sta=9547.16,10452.85
Exp/Cntr=0.3,0.1