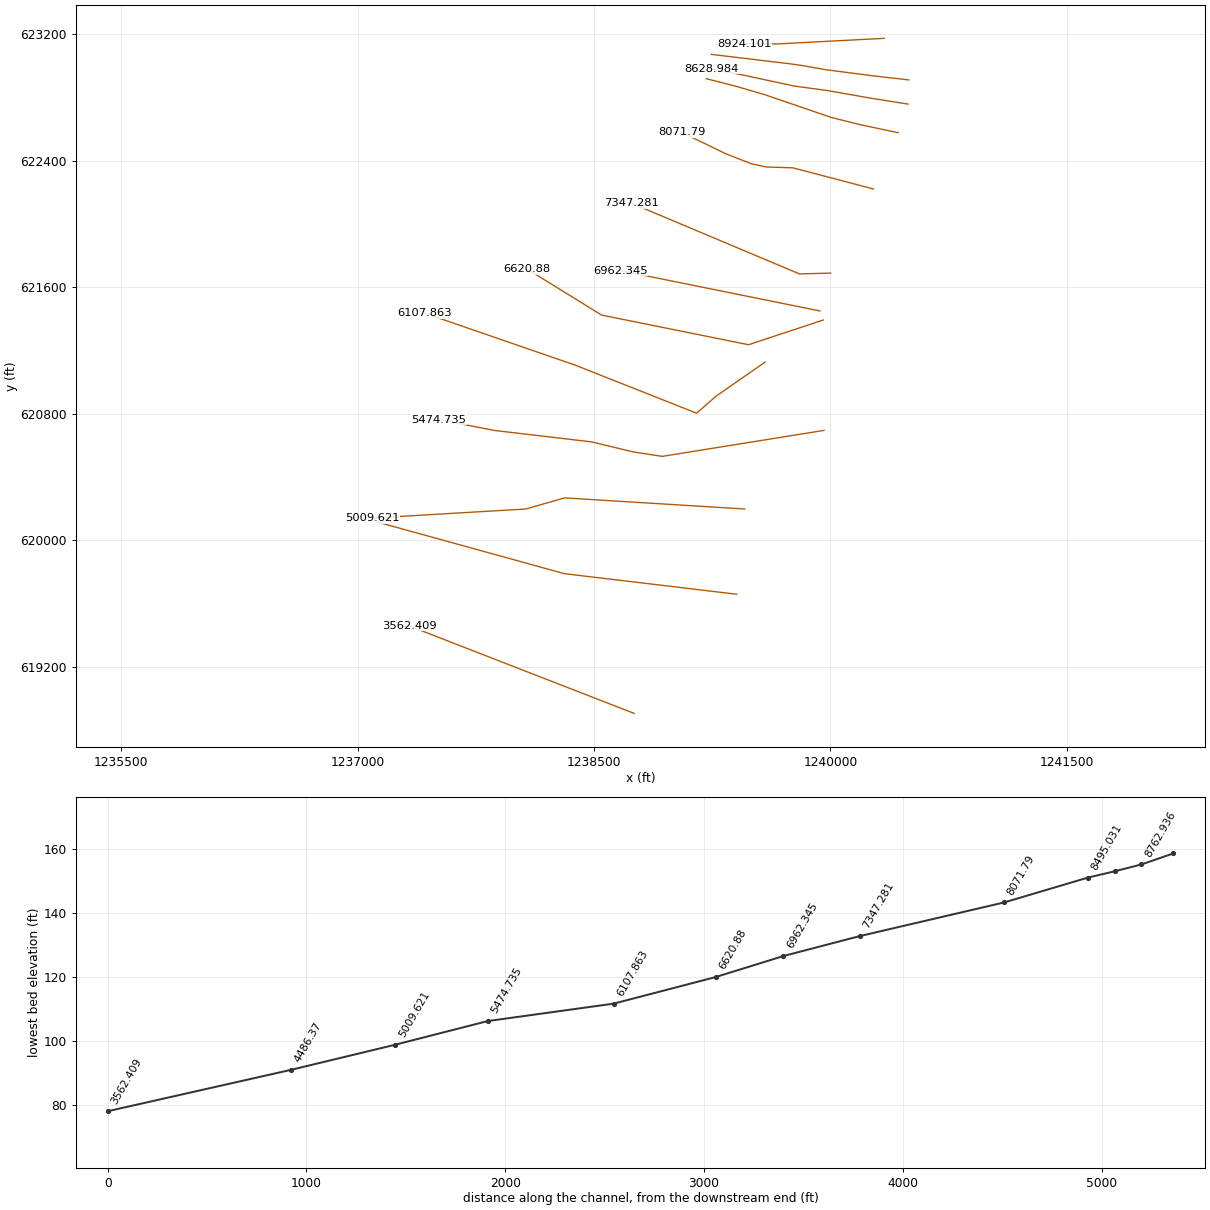
HEC-RAS study 337_ras.prj: 337

--- 337_ras.g01 (geometry) --- (continued)

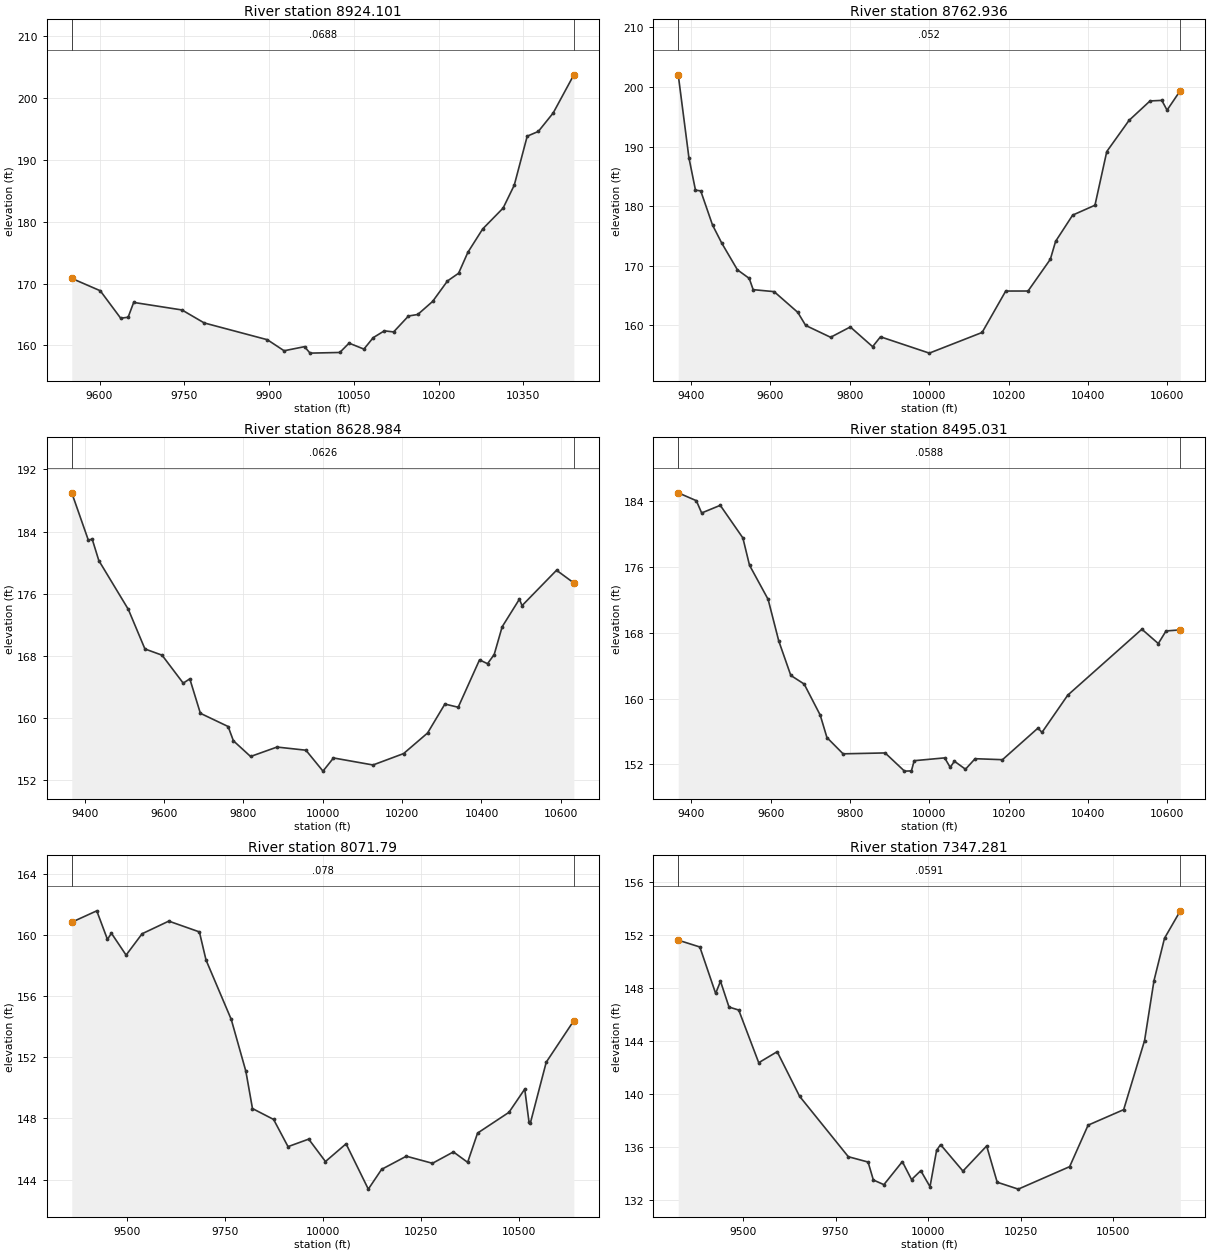
Type RM Length L Ch R = 1 ,8924.101,161.164800,161.164800,161.164800
XS GIS Cut Line= 3
1240340.78815219  623175.21453541239661.17577234623139.883004948
1239453.34324032 623141.96133028
#Sta/Elev= 30
 9550.89170.83929601.314168.84089637.452164.39969650.593164.55929660.449166.9537
9745.866165.73489785.289163.63539896.988160.92169926.555159.13869962.693159.8007
9972.549158.755810025.11158.862110041.54160.368710067.82 159.40910084.25161.2571
10103.96162.358310120.39162.183810146.67 164.75810163.09165.003710189.38167.1136
10215.66170.423310235.36171.671910251.77175.057610278.02178.839710314.11182.2078
10333.79185.900810356.76193.833910376.45194.5995 10402.7197.582810439.26203.7525
#Mann= 3 , 0 , 0
 9550.89  0.0688       0 9550.89  0.0688       010439.26  0.0688       0
#XS Ineff= 2 , 0
       0                               0
Bank Sta=9550.89,10439.26
Exp/Cntr=0.3,0.1

Type RM Length L Ch R = 1 ,8762.936,133.952500,133.952500,133.952500
XS GIS Cut Line= 6
1240497.63727023 622912.108635091240266.93787908622938.457294633
1239972.12094177 622976.51960743 1239821.4905043623003.001056984
1239744.12034809 623014.000829391239243.47049684 623073.94906791
#Sta/Elev= 30
9367.587202.0452 9394.52188.11429411.031182.6697 9424.24182.55149453.959176.8144
9477.074173.7902  9516.7169.2857 9546.42167.85219556.326165.95739609.178165.6236
9668.723162.14629688.571159.94989751.424157.95759801.045159.69239857.282156.3812
9877.131 158.03710000.12155.294510133.08158.764310192.59165.7229 10248.8 165.728
   10305171.061310318.22174.0691 10361.2178.4779 10417.4  180.1410447.15189.1559
10503.27194.3933 10556.1197.655110585.81197.753210599.02 196.11110632.41199.3982
#Mann= 3 , 0 , 0
9367.587   0.052       09367.587   0.052       010632.41   0.052       0
#XS Ineff= 2 , 0
       0                               0
Bank Sta=9367.587,10632.41
Exp/Cntr=0.3,0.1

Type RM Length L Ch R = 1 ,8628.984,133.952500,133.952500,133.952500
XS GIS Cut Line= 6
1240492.27632827622759.2745747091240266.58979681622794.940083133
1239971.27958946622846.4330915021239771.96645519622872.969411028
1239436.06489925622944.9095967361239246.96327522622982.119424256
#Sta/Elev= 30
9367.198188.98559408.791182.91489418.756183.01429435.363180.26799509.835173.9703
9551.618168.88179594.798168.08219648.081164.48069664.732165.03159691.375160.5994
9761.312158.89629774.633157.05739817.928155.03599884.535156.25189957.413155.8457
10000.45153.152210026.93154.848510126.54153.944310203.61155.411110264.05158.0594
10307.71161.788410341.29161.377710395.02167.476910415.17166.985210431.96168.1564
10452.05171.733610495.52175.291710502.21174.460510589.15179.016210632.78177.3813
#Mann= 3 , 0 , 0
9367.198  0.0626       09367.198  0.0626       010632.78  0.0626       0
#XS Ineff= 2 , 0
       0                               0
Bank Sta=9367.198,10632.78
Exp/Cntr=0.3,0.1

Type RM Length L Ch R = 1 ,8495.031,423.241200,423.241200,423.241200
XS GIS Cut Line= 6
1240430.25657605622578.1104954351240187.10177258 622629.45836748
1240004.02107269622675.1783715221239584.45477561622818.428540064
1239401.86782122622871.517475122 1239212.2200447622919.955256132
#Sta/Elev= 30
9366.698184.96099412.364184.00699425.777182.51679472.722183.44419529.726179.4911
9546.492176.17739593.437172.03619620.292166.98799650.652162.80779684.385 161.759
9724.865157.99189741.833155.26599782.558153.29259888.666153.39949937.436151.1922
9954.945151.21959961.948152.457910038.87152.800310052.85151.643910063.35152.3954
10091.32 151.42410115.67152.700410184.68152.579910274.13156.410510284.38155.8936
 10349.3160.408210536.33168.410810577.77166.672210597.28168.200810633.31168.3309
#Mann= 3 , 0 , 0
9366.698  0.0588       09366.698  0.0588       010633.31  0.0588       0
#XS Ineff= 2 , 0
       0                               0
Bank Sta=9366.698,10633.31
Exp/Cntr=0.3,0.1

Type RM Length L Ch R = 1 , 8071.79,724.509000,724.509000,724.509000
XS GIS Cut Line= 6
1240273.18029881 622222.307545771239761.59015741622356.280106192
1239591.00995455622361.7016688881239499.40506207622381.645650267
1239336.63679677622444.9079852871239055.93301571622580.637186746
#Sta/Elev= 30
9359.704160.83919423.451 161.5849450.662 159.7169460.866 160.116 9498.28158.6869
9539.096160.08339607.123160.91049685.193160.20439702.127158.36559766.477154.4765
9803.732151.08579820.588148.6454 9874.48147.93279911.264146.15269964.022 146.645
10006.73145.178210059.28146.336910116.04143.372310149.99144.666910212.98145.5265
10279.66145.062710333.12145.807210369.38 145.126 10394.7147.039410474.84148.3996
10515.03149.919610525.99147.741110529.64147.725710569.83151.677610640.26154.3981
#Mann= 3 , 0 , 0
9359.704   0.078       09359.704   0.078       010640.26   0.078       0
#XS Ineff= 2 , 0
       0                               0
Bank Sta=9359.704,10640.26
Exp/Cntr=0.3,0.1

Type RM Length L Ch R = 1 ,7347.281,384.936400,384.936400,384.936400
XS GIS Cut Line= 3
 1240000.9777889621690.4722811281239803.06112224621685.263947785
1238735.35278893622133.180614442
#Sta/Elev= 30
9325.178151.58619383.512151.07229426.178147.57839439.306148.4956 9462.28 146.552
9488.535 146.327 9542.55142.3633 9592.36143.19349652.843 139.8389784.483135.2893
9837.851134.88789852.082133.53819880.545133.18619930.354134.91889955.259133.5673
9980.164134.239910005.07133.031610022.86135.764610033.53136.199410094.01134.2076
10158.06136.098510186.52  133.3710243.44132.8496 10382.2134.541310432.01137.6637
10528.07138.830610584.51144.029410609.95148.542410638.36151.730810681.02153.7934
#Mann= 3 , 0 , 0
9325.178  0.0591       09325.178  0.0591       010681.02  0.0591       0
#XS Ineff= 2 , 0
       0                               0
Bank Sta=9325.178,10681.02
Exp/Cntr=0.3,0.1

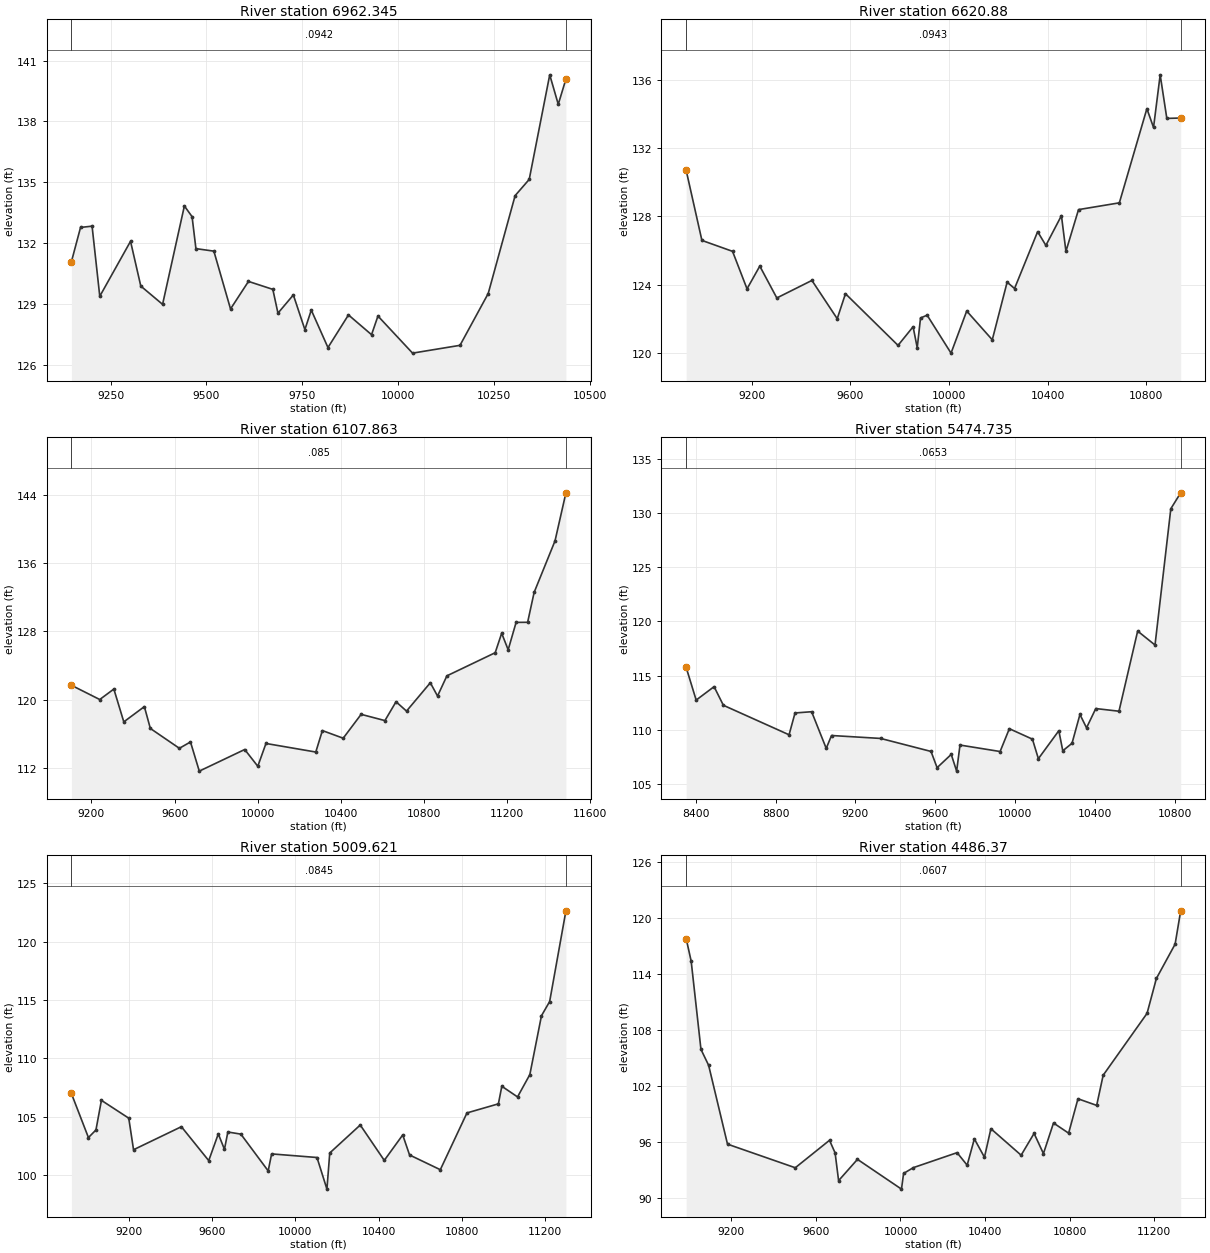
Type RM Length L Ch R = 1 ,6962.345,341.464700,341.464700,341.464700
XS GIS Cut Line= 2
1239933.26945555  621450.88894781238667.64445555621706.097281128
#Sta/Elev= 30
9147.288131.08349171.173132.77779201.295132.84089221.376 129.3839301.701132.0947
9328.476 129.8889385.373128.9864 9442.27133.83649462.351133.30879472.392131.7332
9519.248131.60949562.757128.76029609.613130.11699673.204129.72499686.591 128.552
9726.754129.45049756.876 127.742 9773.61128.70239817.119126.85679870.669128.4652
9930.913127.49099947.647128.410410038.01126.582110161.85126.966310235.48129.5193
10305.76134.345610342.58135.145410396.13   140.310418.39138.845910438.39140.0891
#Mann= 3 , 0 , 0
9147.288  0.0942       09147.288  0.0942       010438.39  0.0942       0
#XS Ineff= 2 , 0
       09461.544                       0
Bank Sta=9147.288,10438.39
Exp/Cntr=0.3,0.1

Type RM Length L Ch R = 1 , 6620.88,513.017300,513.017300,513.017300
XS GIS Cut Line= 4
 1239954.1027889621393.5972811281239480.14445558621237.347281128
1238547.85278893621424.8472811281238073.89445555621716.513947785
#Sta/Elev= 30
8933.645130.70298997.507126.5926 9121.87125.95099180.597123.75269232.415125.0856
9301.505123.21679443.855124.24589546.556122.00059580.021123.46639793.288120.4363
9854.437121.52879871.169120.29779884.555122.04279911.328122.208110008.38119.9822
10071.96122.4503 10175.7120.764510235.94124.142210266.06 123.77210359.76127.1051
10393.17126.298510456.31128.045310474.55125.951310525.65128.3981 10691.3128.7958
10803.02134.316610829.98133.213610856.95136.302310883.92133.746210940.17133.7695
#Mann= 3 , 0 , 0
8933.645  0.0943       08933.645  0.0943       010940.17  0.0943       0
#XS Ineff= 2 , 0
       09526.799                       0
Bank Sta=8933.645,10940.17
Exp/Cntr=0.3,0.1

Type RM Length L Ch R = 1 ,6107.863,633.127800,633.127800,633.127800
XS GIS Cut Line= 5
 1239585.6632857621128.043283612 1239272.0615229620910.545286819
1239150.66729212620804.325334892 1238381.8371639621107.810911819
1237425.85759658621436.586953476
#Sta/Elev= 30
9103.334121.69169239.827120.02499307.703121.24919355.615117.40869454.579119.1945
9483.364116.64049623.084 114.3179676.612115.05959718.938111.64599937.624 114.176
10000.63112.214910039.91114.882410279.76113.879710311.51116.390910411.67115.4969
10498.03118.290710612.52117.558510666.06119.7653 10716.5118.668910831.09121.9853
10865.79120.432210910.89122.795511143.34125.500911174.57127.783311205.79 125.841
11243.96129.049911299.47129.060811330.69132.555111431.31138.587911483.78144.2097
#Mann= 3 , 0 , 0
9103.334   0.085       09103.334   0.085       011483.78   0.085       0
#XS Ineff= 2 , 0
       09650.072        10348.57       0
Bank Sta=9103.334,11483.78
Exp/Cntr=0.3,0.1

Type RM Length L Ch R = 1 ,5474.735,465.113700,465.113700,465.113700
XS GIS Cut Line= 6
1239959.31112224620695.6806144571238932.81108344 620531.23815918
1238746.94695064620559.7875755281238485.35278893620622.763947785
1237869.53552535 620694.96321319 1237516.6027889620763.388947785
#Sta/Elev= 30
8352.609115.75888402.695112.74178492.407113.98118538.925112.26378867.868109.5418
8897.772111.55418980.839111.66939053.938108.28749080.519109.47479326.396109.2041
 9578.73108.00439609.076106.50599679.942107.73169706.939 106.1889723.812108.5937
 9924.66107.99729970.906110.102110086.52109.137610116.25107.335510218.65109.9169
10238.47108.063710284.72108.758810324.36111.414810357.39 110.18310403.64111.9609
10519.84111.715810613.41  119.11 10700.3 117.82310779.44130.397410828.85131.8656
#Mann= 3 , 0 , 0
8352.609  0.0653       08352.609  0.0653       010828.85  0.0653       0
#XS Ineff= 2 , 0
       09408.647        10072.66       0
Bank Sta=8352.609,10828.85
Exp/Cntr=0.3,0.1

Type RM Length L Ch R = 1 ,5009.621,523.251100,523.251100,523.251100
XS GIS Cut Line= 4
1239456.86532176620198.350292623 1238313.6361551620268.662792623
1238066.24032179620198.3502926231237092.28198847620141.058625951
#Sta/Elev= 30
 8922.58106.9746 9004.52103.19759040.678103.84929066.974 106.3879198.455104.8589
9221.464102.15479451.557104.12859583.029101.22149629.056103.5107 9658.64102.1881
9675.075103.67439737.529103.4914 9869.01100.34079885.445101.797110103.68101.4885
10151.4498.7781310165.08101.876610311.74104.273110427.26101.241110515.99103.4227
10548.86101.705410696.75100.442410824.93 105.309 10976.1106.087410992.54107.5949
11068.13106.680811127.28108.593111183.15113.635211222.59114.8574 11300.8122.6296
#Mann= 3 , 0 , 0
 8922.58  0.0845       0 8922.58  0.0845       0 11300.8  0.0845       0
#XS Ineff= 2 , 0
       09741.235        10266.38       0
Bank Sta=8922.58,11300.8
Exp/Cntr=0.3,0.1

Type RM Length L Ch R = 1 , 4486.37,923.961000,923.961000,923.961000
XS GIS Cut Line= 3
1239405.16233659619659.2488390511238311.41233662619789.457172379
 1237118.7040033620117.582172394
#Sta/Elev= 30
 8986.67 117.7929010.357115.37589056.613105.90859092.957104.19599182.16595.73859
9502.65393.207269664.54996.153899690.98194.800429707.50191.824039796.70994.10884
10004.8690.9138910014.77 92.595510061.0393.2205210267.79 94.826110315.4293.48188
10349.45 96.303410397.2294.3359310427.7197.3949110570.6394.5529210631.8896.89181
10676.1194.7242510723.7598.0088310795.2196.9186910839.44100.608710927.91  99.897
10958.54103.1316 11166.1  109.7711210.34113.518211298.81 117.19711325.16120.7714
#Mann= 3 , 0 , 0
 8986.67  0.0607       0 8986.67  0.0607       011325.16  0.0607       0
#XS Ineff= 2 , 0
       09662.147        10450.77       0
Bank Sta=8986.67,11325.16
Exp/Cntr=0.3,0.1

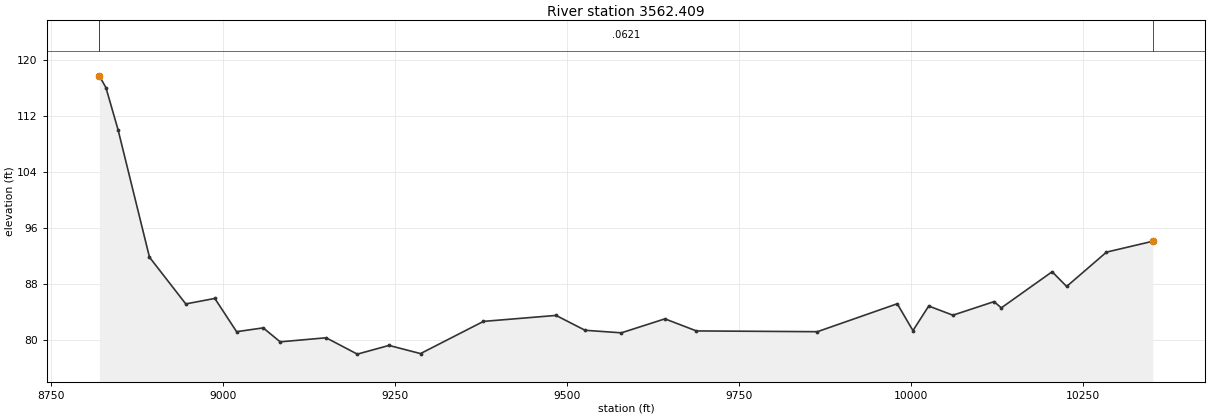
Type RM Length L Ch R = 1 ,3562.409,0.000000,0.000000,0.000000
XS GIS Cut Line= 2
1238754.08851972618905.808767036 1237325.9442296619459.403160051
#Sta/Elev= 30
8819.697 117.7718829.273116.08078846.867110.0701 8892.6191.79389 8945.3985.10377
8987.61585.888819019.28381.126349057.98981.67207 9082.6279.672159149.47580.25253
9194.82277.912849240.96179.159249286.70477.98993 9378.1982.600269483.75183.45734
9525.97681.328189578.75680.963999642.09382.963819687.83681.23637 9863.7781.12525
9979.88785.1268410002.7181.2798910025.6384.8034510060.8283.4887310120.6485.43317
10131.1984.5390510205.0889.71136 10226.287.6040410284.1192.5209410351.3894.07934
#Mann= 3 , 0 , 0
8819.697  0.0621       08819.697  0.0621       010351.38  0.0621       0
#XS Ineff= 2 , 0
       0                               0
Bank Sta=8819.697,10351.38
Exp/Cntr=0.3,0.1